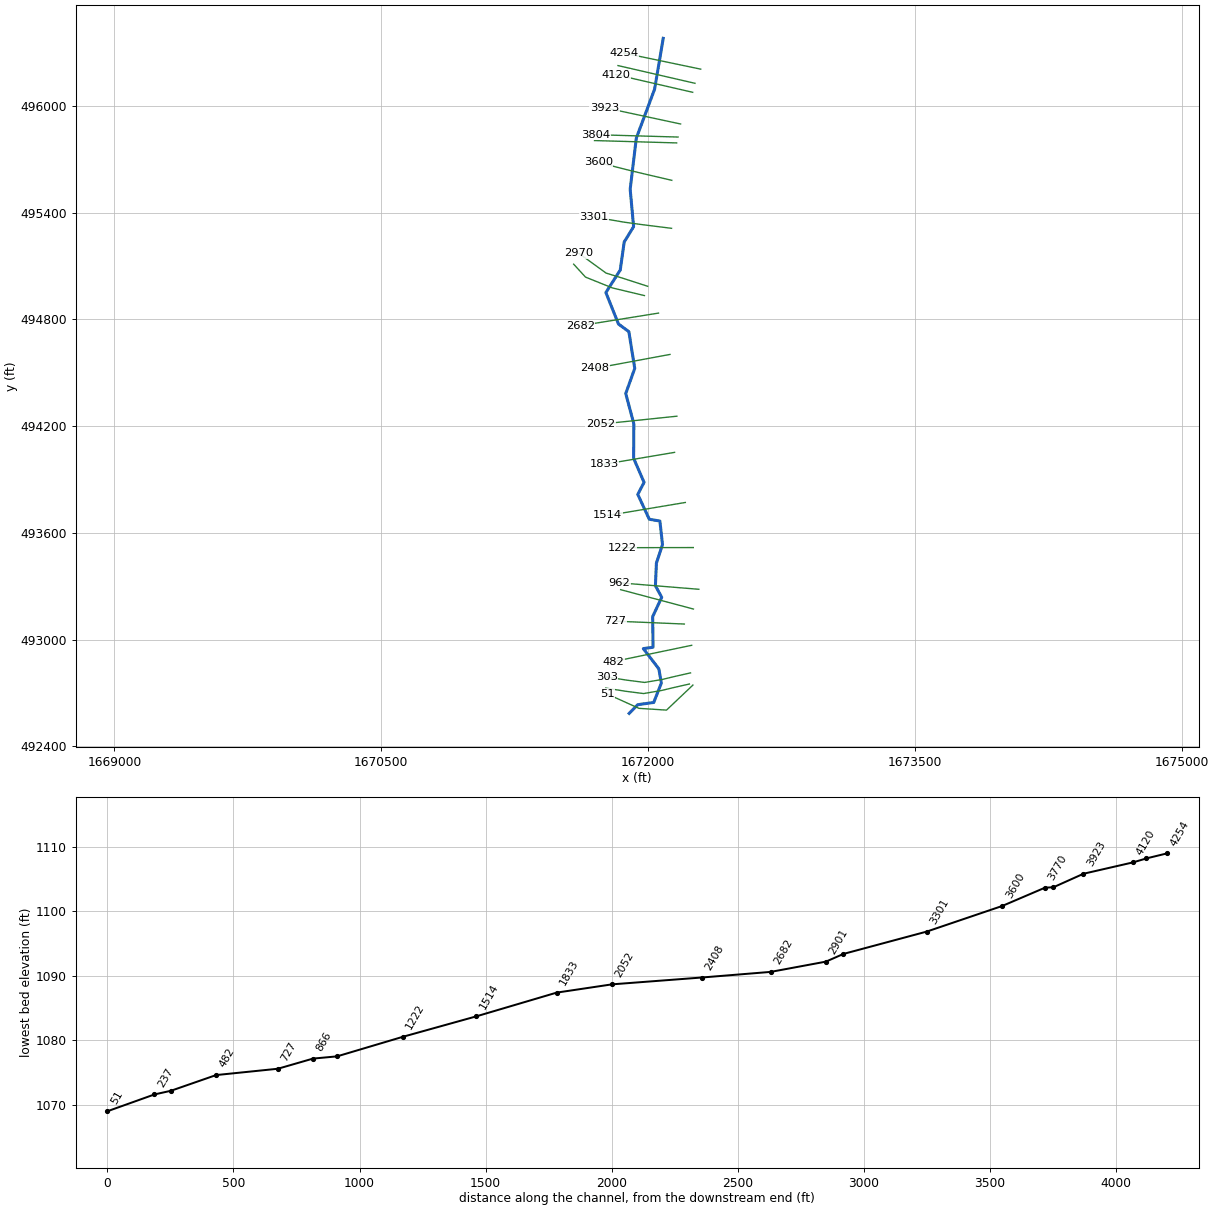
--- NFGraveCkT2.prj (project) ---

Proj Title=NFGraveCkT2
Current Plan=p01
Default Exp/Contr=0,0
English Units
Geom File=g01
Flow File=f01
Plan File=p01
BEGIN DESCRIPTION:
---------- MODELED AS PART OF WVEM CTP PROGRAM, 2025----------
Stream Name: North Fork Grave Creek Tributary 2
Flood Zone: AFH
Marshall County, WV
HEC-RAS Version: RAS 6.6
Vertical Datum: NAVD88
Projection: NAD 1983 StatePlane West Virginia N FIPS 4701 (US Feet)
Terrain: 1-meter West Virginia FEMA R3 South Central (collected 2018-2019)
Land Use: 2024 NLCD
Hydrologic Method:
Duda et al., "Estimation of magnitude and frequency of floods for rural, unregulated streams in and near Virginia and West Virginia." September 8, 2025.
Additional Model Notes:
None
END DESCRIPTION:
DSS Export Rating Curves= 0
DSS Export Rating Curve Sorted= 0
DSS Export Volume Flow Curves= 0
DXF OffsetX= 0
DXF OffsetY= 0
DXF ScaleX= 0
DXF ScaleY= 0

--- NFGraveCkT2.p01 (plan) ---

Plan Title=Floodplain
Program Version=6.60
Short Identifier=Floodplain
Geom File=g01
Flow File=f01
Subcritical Flow
K Sum by GR= 0
Std Step Tol= 0.01
Critical Tol= 0.01
Num of Std Step Trials= 20
Max Error Tol= 0.3
Flow Tol Ratio= 0.001
Split Flow NTrial= 30
Split Flow Tol= 0.02
Split Flow Ratio= 0.02
Log Output Level= 0
Friction Slope Method= 1
Unsteady Friction Slope Method= 2
Unsteady Bridges Friction Slope Method= 1
Parabolic Critical Depth
Global Vel Dist= 0 , 0 , 0
Global Log Level= 0
CheckData=False
Encroach Param=-1 ,0,0, 0
Flow Ratio Tolerance=0.1
Flow Ratio Min Ratio=0.5
Flow Ratio Max Ratio=4
Flow Ratio Max Iterations= 10
Mapping Interval=1HOUR
Computation Time Step Use Courant=        0
Computation Time Step Use Time Series=    0
Computation Time Step Count To Double=0
Computation Time Step Max Doubling=0
Computation Time Step Max Halving=0
Computation Time Step Residence Courant=0
Run HTab= 0
Run UNet= 0
Run Sediment= 0
Run PostProcess= 0
Run WQNet= 0
Run RASMapper=-1
UNET Theta= 0
UNET Theta Warmup= 0
UNET ZTol= 0
UNET ZSATol= 0
UNET MxIter= 0
UNET Max Iter WO Improvement= 0
UNET MaxInSteps= 0
UNET DtIC= 0
UNET DtMin= 0
UNET MaxCRTS= 0
UNET WFStab= 0
UNET SFStab= 0
UNET WFX= 1
UNET SFX= 1
UNET Gravity=32.17405
UNET 1D Methodology=Finite Difference
UNET DSS MLevel= 1
UNET Pardiso=0
UNET DZMax Abort= 0
UNET Use Existing IB Tables= 0
UNET Froude Reduction=False
UNET Froude Limit= 0
UNET Froude Power= 0
UNET D1 Cores= 0
UNET WindReference=Eulerian
UNET WindDragFormulation=Hsu (1988)
UNET D2 Coriolis=0
UNET D2 Cores= 0
UNET D2 Theta= 1
UNET D2 Theta Warmup= 1
UNET D2 Z Tol= 0.01
UNET D2 Volume Tol= 0.01
UNET D2 Max Iterations= 20
UNET D2 Advanced Convergence=0
UNET D2 WS Max Tol=0.15
UNET D2 WS RMS Tol=0.002
UNET D2 WS Stall Tol=1
UNET D2 Equation= 0
UNET D2 RampUpFraction=0.1
UNET D2 TimeSlices= 1
UNET D2 Turbulence Formulation=Non-Conservative (original)
UNET D2 Eddy Viscosity=0.3
UNET D2 Transverse Eddy Viscosity=0.1
UNET D2 Smagorinsky Mixing=0
UNET D2 BCVolumeCheck=0
UNET D2 Cores=0
UNET D2 SolverType=PARDISO (Direct)
UNET D2 Minimum Iterations= 3
UNET D2 Maximum Iterations= 30
UNET D2 Restart Number= 10
UNET D2 Relaxation Coeff=1.3
UNET D2 SOR Precondition Iterations= 10
UNET D2 ILUT Maximum Fill= 8
UNET D2 ILUT Tolerance=1E-08
UNET D2 Convergence Tolerance=0.00001
PS Theta= 1
PS WS Tol= 0.01
PS Volume Tol= 0.01
PS Max Iterations= 20
PS Equation= 0
PS Advance Time Step=-1
PS Target Courant=0.9
PS Time Slices= 1
PS Iterate With 2D=0
PS Project Initial WSE from DS=-1
PS Ramp Up Initial WSE from US=-1
PS Cores=0
UNET D1D2 MaxIter= 0
UNET D1D2 ZTol=0.01
UNET D1D2 QTol=0.1
UNET D1D2 MinQTol=1
Write IC File= 0
Write IC File at Fixed DateTime=0
Write IC File at Sim End=0
Echo Input=False
Echo Parameters=False
Echo Output=False
Write Detailed= 0
HDF Write Warmup=0
HDF Write Time Slices=0
HDF Flush=0
HDF Compression= 1
HDF Chunk Size= 1
HDF Spatial Parts= 1
HDF Use Max Rows=0
HDF Fixed Rows= 1
Calibration Method= 0
Calibration Iterations= 20
Calibration Max Change=0.05
Calibration Tolerance=0.2
Calibration Maximum=1.5
Calibration Minimum=0.5
Calibration Optimization Method= 1
WQ AD Non Conservative
WQ ULTIMATE=-1
WQ Max Comp Step=1HOUR
WQ Output Interval=15MIN
WQ Output Selected Increments= 0
WQ Create Restart=0
WQ Fixed Restart=0
WQ System Summary=0
WQ Write To DSS=0
Sorting and Armoring Iterations= 10
XS Update Threshold= 0.02
Bed Roughness Predictor= 0
Processes Affected by Predictor=Sediment Only
Hydraulics Update Threshold= 0.02
Energy Slope Method= 1
Volume Change Method= 1
Sediment Retention Method= 0
Sediment TS Multiplier= 1
Warm Up Method= 0
XS Weighting Method= 0
Number of US Weighted Cross Sections= 1
Number of DS Weighted Cross Sections= 1
Upstream XS Weight=0
Main XS Weight=1
Downstream XS Weight=0
Number of DS XS's Weighted with US Boundary= 1
Upstream Boundary Weight= 1
Weight of XSs Associated with US Boundary= 0
Number of US XS's Weighted with DS Boundary= 1
Downstream Boundary Weight= 0.5
Weight of XSs Associated with DS Boundary= 0.5
Percentile Method= 0
Sediment Output Level= 3
Mass or Volume Output= 0
Output Increment Type= 1
Profile and TS Output Increment= 1
Transport Output Increment 1
XS Output Flag= 0
XS Output Increment= 10
Read HDF5 Sediment Hotstart= 0
Sediment Hotstart Type= 0
Write Gradation File= 0
Read Gradation Hotstart= 0
Write HDF5 File= 1
Write Binary Output= 1
Write DSS Sediment File= 0
DSS Sediment Output Type= 1
SV Curve= 0
Specific Gage Flag= 0
Subcell Erosion Methods= 0
Subcell Deposition Methods= 0
Advection Scheme= 1
Matrix Solver= 0
Implicit Weighting Factor= 1
Maximum Outer Loop Convergence Iterations= 5
Convergence Maximum Absolute= 0.001
Convergence RMSE= 0.0001
Grain Fractions Max Abs Error= 0.001
Max Subgrid Regions= 1
Max Subgrid Length Scale= 3.402823E+38
Initial Layer Thickness= 3
Min Layer Thickness= 0.1
Max Layer Thickness= 6
Number of Layers= 5

--- NFGraveCkT2.f01 (steady flow) ---

Flow Title=Flow
Program Version=6.60
Number of Profiles= 1
Profile Names=P100yr
River Rch & RM=NFGraveCkT2,Main            ,4254
     864
Boundary for River Rch & Prof#=NFGraveCkT2,Main            , 1
Up Type= 0
Dn Type= 3
Dn Slope=0.018666
DSS Import GetInterval= 0
DSS Import GetPeak= 0
DSS Import FillOption= 0

--- NFGraveCkT2.g01 (geometry) ---

Geom Title=Geometry
Program Version=6.60

River Reach=NFGraveCkT2     ,Main
Reach XY= 30
     1672085.446      496380.881     1672037.068      496095.459
     1671934.145      495819.819     1671899.649       495532.57
     1671918.902      495321.912     1671866.049      495235.837
     1671843.775      495078.031      1671763.08      494951.514
     1671833.865      494774.549     1671892.263      494731.488
      1671925.32      494524.959     1671874.732      494383.388
     1671920.272      494213.149     1671919.063      494019.496
     1671977.727      493884.364     1671942.463      493816.638
     1672007.005      493676.948     1672066.796      493666.639
     1672081.366      493534.135     1672047.146        493430.1
     1672041.516      493302.897      1672077.02       493237.96
     1672026.071      493129.135     1672028.317      492957.019
     1671973.483      492949.471     1672060.729      492835.807
     1672074.937      492755.664     1672032.091      492646.661
     1671942.181      492634.007     1671893.974      492585.257

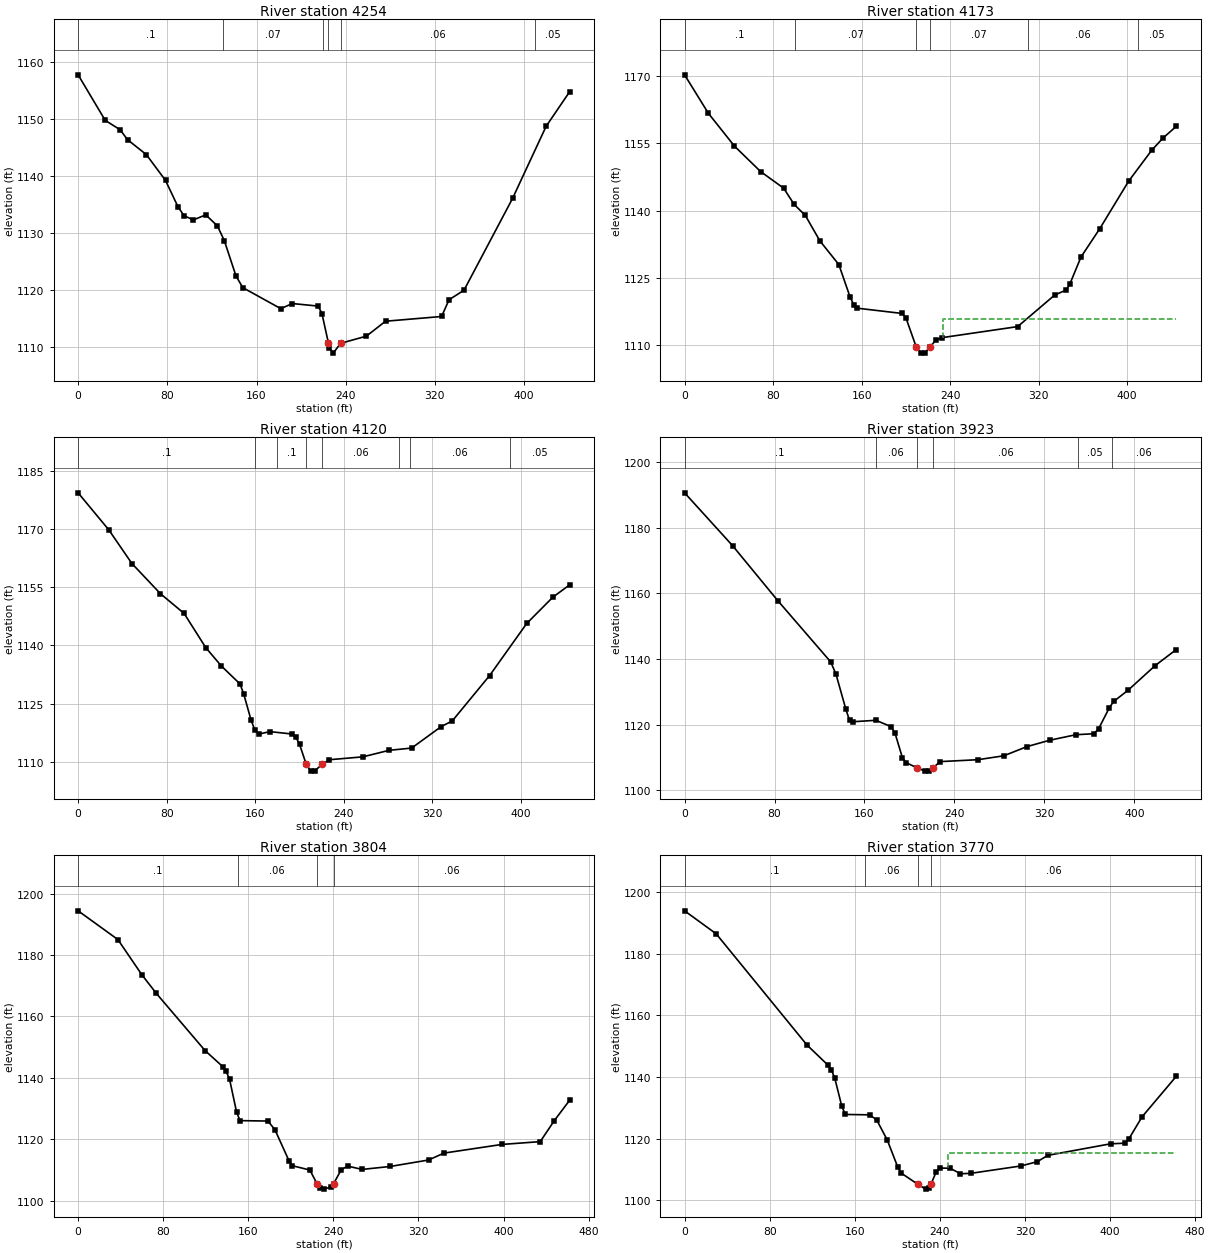
Type RM Length L Ch R = 1 ,4254    ,81.2,81.2,80.9
XS GIS Cut Line= 2
1672296.37937448496207.6036513581671864.85796399496297.846312892
#Sta/Elev= 30
       0 1157.74    24.3 1149.76    37.7 1148.11    44.4 1146.36    61.2 1143.76
    78.4 1139.23    89.5 1134.64      95 1133.05   103.4 1132.32   114.5  1133.2
   124.9 1131.27   131.1  1128.7   141.6 1122.49   147.7 1120.45   181.8 1116.76
   192.1 1117.66   215.4 1117.21   218.7 1115.88  224.561110.686   225.4  1109.9
   228.8 1108.97  235.411110.683   258.6 1111.95   275.7 1114.56     326 1115.39
   332.7 1118.33   346.1 1119.99   389.7  1136.1   419.8 1148.73   440.9 1154.79
#Mann= 6 ,-1,0
       0      .1       0     130     .07       0     220     .06       0
  224.56    .045       0  235.41     .06       0     410     .05       0
Bank Sta=224.56,235.41
XS Rating Curve= 0 ,0
Exp/Cntr=0.3,0.1

Type RM Length L Ch R = 1 ,4173    ,52.3,52.3,52.2
XS GIS Cut Line= 2
1672264.08709817496128.0598788411671831.23185288496227.685992762
#Sta/Elev= 30
       0 1170.28    21.6 1161.66    45.1 1154.37    68.7  1148.7    89.5    1145
      99 1141.38   109.1 1138.91   122.3 1133.23   139.4 1127.95   149.5 1120.74
   152.9 1118.98   156.2 1118.22   196.6 1117.05     200 1116.08  209.181109.672
   213.5 1108.27   216.8  1108.2  222.211109.671   226.9 1111.08   232.3 1111.64
     301 1114.12   334.7 1121.21   344.8 1122.26   348.1 1123.59   358.2 1129.64
   375.1 1135.93   401.4 1146.61   422.2 1153.48   432.3 1156.18   444.2 1158.76
#Mann= 6 ,-1,0
       0      .1       0     100     .07       0  209.18    .045       0
  222.21     .07       0     310     .06       0     410     .05       0
#XS Ineff= 2 , 0
                          233.57         1115.75
Permanent Ineff=
       F       F
Bank Sta=209.18,222.21
XS Rating Curve= 0 ,0
Exp/Cntr(USF)=0,0
Exp/Cntr=0.3,0.1

Type RM Length L Ch R = 1 ,4120    ,196.2,197.6,196.5
XS GIS Cut Line= 2
 1672251.0707285496077.4654106561671818.21548321496177.091524576
#Sta/Elev= 30
       0 1179.36    27.8 1169.78    48.6 1161.13    74.3 1153.37    95.8 1148.25
   115.3 1139.46   129.4 1134.71   146.3 1130.07   149.6 1127.53   156.3 1120.73
   159.7 1118.19   163.1 1117.12   173.2 1117.78   193.4 1117.16   196.7 1116.41
   200.1 1114.48  206.18 1109.32   210.2 1107.65   213.6 1107.59  220.431109.324
     227 1110.53   257.3 1111.27   280.9 1112.95   301.4 1113.54     328 1119.06
   338.1 1120.54   371.8 1132.22   405.4 1145.68     429 1152.45   444.2 1155.64
#Mann= 8 ,-1,0
       0      .1       0     160     .07       0     180      .1       0
  206.18    .045       0  220.43     .06       0     290     .07       0
     300     .06       0     390     .05       0
Bank Sta=206.18,220.43
XS Rating Curve= 0 ,0
Exp/Cntr(USF)=0,0
Exp/Cntr=0.3,0.1

Type RM Length L Ch R = 1 ,3923    ,117.7,119.2,120.7
XS GIS Cut Line= 2
1672183.13712884495899.2886828331671755.64792023495990.959430412
#Sta/Elev= 30
       0 1190.62    42.7 1174.51      83 1157.72     130 1139.08   134.7 1135.31
   143.4 1124.71   146.7 1121.27   150.1 1120.88   170.2 1121.31   183.7 1119.36
   187.2 1117.34   193.7 1109.94   197.1  1108.4  206.591106.835   213.9 1105.82
   217.2 1105.93     2211106.833   227.3 1108.72   260.8  1109.3   283.9 1110.49
   304.5 1113.29   324.6 1115.22   348.1 1116.92     364 1117.21   368.2 1118.71
   377.8 1125.15   381.6 1127.05   394.4 1130.46   418.5 1137.97   437.2 1142.84
#Mann= 6 ,-1,0
       0      .1       0     170     .06       0  206.59    .045       0
     221     .06       0     350     .05       0     380     .06       0
Bank Sta=206.59,221
XS Rating Curve= 0 ,0
Exp/Cntr(USF)=0,0
Exp/Cntr=0.3,0.1

Type RM Length L Ch R = 1 ,3804    ,33.6,33.7,33.6
XS GIS Cut Line= 2
1672168.85655706495825.8482575451671706.81024965495839.049580614
#Sta/Elev= 30
       0 1194.37    37.4 1185.01    59.9 1173.56    73.5 1167.49   119.4 1148.84
   136.5 1143.47   139.1 1142.16   142.4 1139.51     149 1128.81   152.2 1126.04
   178.5  1125.9   185.1 1123.06   198.2 1113.02   201.5 1111.35   217.9 1109.95
  224.541105.538   227.7  1104.1     231 1103.73   237.6 1104.43  240.271105.538
   247.4 1110.05   253.4 1111.23   267.1 1110.15   293.4 1111.11   329.5 1113.21
   343.9 1115.46   398.6 1118.29   434.5  1119.2   447.6 1125.98   462.2  1132.7
#Mann= 4 ,-1,0
       0      .1       0     150     .06       0  224.54    .045       0
  240.27     .06       0
Bank Sta=224.54,240.27
XS Rating Curve= 0 ,0
Exp/Cntr(USF)=0,0
Exp/Cntr=0.3,0.1

Type RM Length L Ch R = 1 ,3770    ,170.3,169.4,167.9
XS GIS Cut Line= 2
1672161.15578527495792.8449498731671699.10947786495806.046272942
#Sta/Elev= 30
       0 1193.88    29.7 1186.43     115 1150.41   134.7 1143.89     138 1142.32
   141.2 1139.64   147.8 1130.55   151.1 1127.87   174.1 1127.74   180.6  1126.1
   190.5 1119.64   200.3 1110.93   203.6 1108.87   219.31105.234   226.6 1103.66
   229.9  1104.1  231.641105.231   236.4 1109.12   239.7 1110.49   249.6 1110.44
   259.4 1108.65   268.9 1108.77   316.2 1111.17   331.6 1112.55   341.5 1114.61
   400.5 1118.35   413.7 1118.55   417.5 1119.82   430.1 1127.08   462.2 1140.19
#Mann= 4 ,-1,0
       0      .1       0     170     .06       0   219.3    .045       0
  231.64     .06       0
#XS Ineff= 2 , 0
                          247.29         1115.22
Permanent Ineff=
       F       F
Bank Sta=219.3,231.64
XS Rating Curve= 0 ,0
Exp/Cntr(USF)=0,0
Exp/Cntr=0.3,0.1

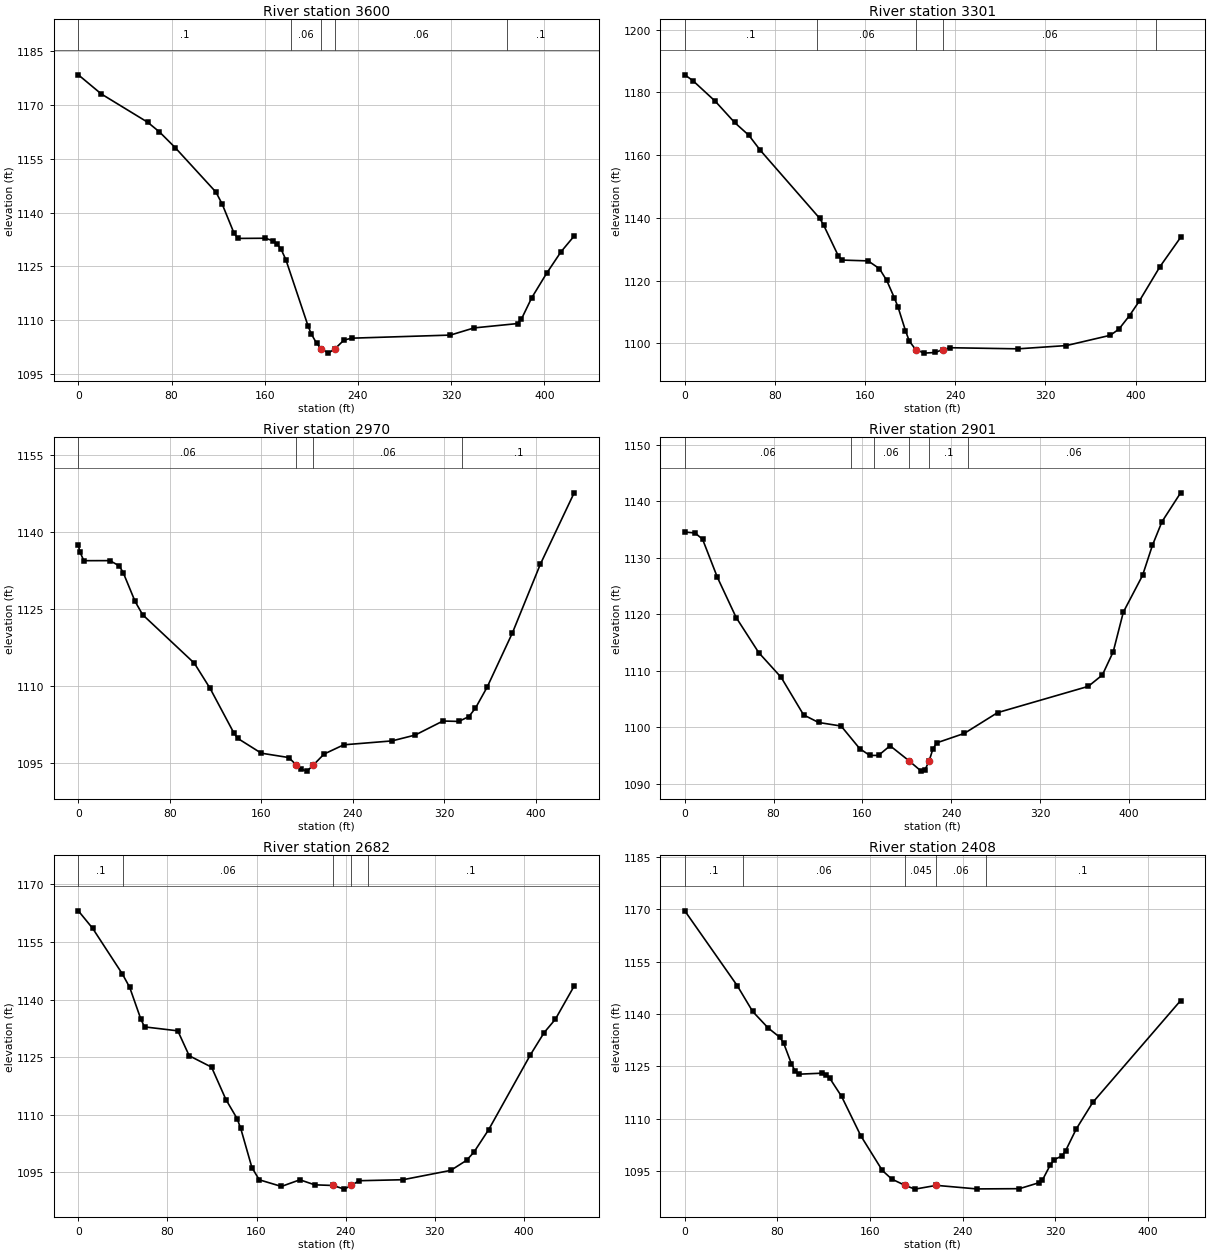
Type RM Length L Ch R = 1 ,3600    ,298.7,299.8,297.4
XS GIS Cut Line= 6
1672133.65658475495582.5324265961672048.48319867495602.392623082
1671975.47153367495619.4158830051671878.14397243495642.904353082
1671805.24549617495661.4614025951671720.24960317495683.321595088
#Sta/Elev= 30
       0 1178.42    19.7 1173.09    59.5  1165.2    69.6 1162.51    83.1 1158.13
   118.1 1145.72   123.5 1142.35   133.6 1134.28     137 1132.81   160.5 1132.86
   167.3 1132.13   170.7  1131.2     174  1129.8   178.1 1126.88   197.1 1108.45
   199.8 1106.24   204.4 1103.62  208.571102.023   214.5 1100.83  220.171102.025
     228 1104.48   234.8    1105   319.3 1105.86   339.6 1107.86   376.9 1109.07
   380.3 1110.36   389.1 1116.27   401.8 1123.05   414.2 1129.08   425.5 1133.48
#Mann= 5 ,-1,0
       0      .1       0  182.43     .06       0  208.57    .045       0
  220.17     .06       0  367.77      .1       0
Bank Sta=208.57,220.17
XS Rating Curve= 0 ,0
Exp/Cntr(USF)=0,0
Exp/Cntr=0.3,0.1

Type RM Length L Ch R = 1 ,3301    ,329.4,330.3,325.2
XS GIS Cut Line= 6
1672132.23303117495312.6838849191672045.40905784495323.539834335
1671970.98860301495332.8449338381671866.74078001495347.062425092
1671787.30097826495360.6778834161671696.83626418495375.669651344
#Sta/Elev= 30
       0  1185.6     7.3 1183.71    27.2 1177.11    44.2  1170.4    56.9  1166.3
    66.9 1161.58   119.8  1139.8   123.1 1137.76   136.3 1127.82   139.6 1126.53
   162.7 1126.27   172.7 1123.79   179.2 1120.04   185.9 1114.53   189.2 1111.58
   195.8 1104.06   199.2  1100.7  204.861098.006   212.4 1096.86   222.3 1097.07
  228.931098.006   235.6 1098.58   295.7 1098.23   338.6 1099.27   377.6 1102.55
   385.2  1104.5   394.7 1108.85   403.3 1113.44   421.7 1124.45     440 1133.77
#Mann= 5 ,-1,0
       0      .1       0   117.5     .06       0  204.86    .045       0
  228.93     .06       0  418.31      .1       0
Bank Sta=204.86,228.93
XS Rating Curve= 0 ,0
Exp/Cntr(USF)=0,0
Exp/Cntr=0.3,0.1

Type RM Length L Ch R = 1 ,2970    ,69.5,69.4,68.6
XS GIS Cut Line= 4
  1671998.283759494986.6432896031671861.07917154495031.078614453
1671764.12665714495060.9915471091671612.09744862495171.183839843
#Sta/Elev= 30
       0 1137.45     1.3 1136.18     4.8 1134.43    27.6 1134.44    35.8 1133.41
    39.3 1132.06    49.6 1126.49    56.2  1123.9   101.4 1114.44   115.2 1109.52
   135.8  1100.9   139.3 1099.79   159.9  1096.9   183.9 1096.05  190.65 1094.58
   194.2 1093.82   199.9  1093.4  205.39 1094.58   214.8 1096.73     232 1098.53
   274.1 1099.29   294.4 1100.43   318.7 1103.17   332.5 1103.09   341.3 1104.02
   347.1 1105.67   357.4  1109.8   379.5 1120.39   403.8 1133.72   433.4 1147.66
#Mann= 4 ,-1,0
       0     .06       0  190.65    .045       0  205.39     .06       0
  335.68      .1       0
Bank Sta=190.65,205.39
XS Rating Curve= 0 ,0
Exp/Cntr(USF)=0,0
Exp/Cntr=0.3,0.1

Type RM Length L Ch R = 1 ,2901    ,208.3,219.1,219.5
XS GIS Cut Line= 4
1671979.72190444494934.4908959681671800.07979907494977.324142292
1671648.56796802495038.2573232541671581.95143307495111.011642443
#Sta/Elev= 30
       0 1134.52     9.2 1134.36      16 1133.25    29.4 1126.48    46.3 1119.38
    66.6 1113.18    86.8  1108.8     107 1102.16   120.5 1100.82   140.8 1100.19
   157.6 1096.18   166.7 1094.98   174.5    1095   184.9  1096.7  201.711094.078
   212.9 1092.21   216.4 1092.45  220.191094.077   223.5 1096.16     227 1097.22
   251.8 1098.89   281.7 1102.56   363.4 1107.21   376.1 1109.22   385.9 1113.34
     395 1120.35   412.3 1126.84   421.2 1132.17   429.8 1136.35   446.6 1141.46
#Mann= 6 ,-1,0
       0     .06       0     150      .1       0     170     .06       0
  201.71    .045       0  220.19      .1       0  254.68     .06       0
Bank Sta=201.71,220.19
XS Rating Curve= 0 ,0
Exp/Cntr(USF)=0,0
Exp/Cntr=0.3,0.1

Type RM Length L Ch R = 1 ,2682    ,271.5,273.4,269.2
XS GIS Cut Line= 2
1672058.92557469494835.9451982571671619.44065599494765.500735982
#Sta/Elev= 30
       0 1163.11    12.9 1158.53    39.5 1146.68    46.1 1143.18    56.1 1134.91
    59.4 1132.88    89.3 1131.85    99.5 1125.37   119.6 1122.39   132.5 1113.95
   142.5    1109   145.8 1106.42   155.8 1096.25   162.4 1093.05   182.3 1091.32
   198.9 1093.05   212.2 1091.74  228.63 1091.57   238.8 1090.62  244.841091.565
   252.1 1092.81   291.4 1093.07   334.3  1095.5   348.5 1098.12   355.1 1100.24
   368.4 1106.13   405.9 1125.64   418.2 1131.41   428.2 1134.86   445.1 1143.52
#Mann= 5 ,-1,0
       0      .1       0      40     .06       0  228.63    .045       0
  244.84     .06       0     260      .1       0
Bank Sta=228.63,244.84
XS Rating Curve= 0 ,0
Exp/Cntr(USF)=0,0
Exp/Cntr=0.3,0.1

Type RM Length L Ch R = 1 ,2408    ,355.4,356,352.2
XS GIS Cut Line= 2
1672123.51885702494603.5694414081671702.46683034494525.393137514
#Sta/Elev= 30
       0  1169.6    45.3 1148.12    58.6 1140.73      72 1135.98      82 1133.34
    85.3  1131.7      92 1125.79    95.3 1123.54    98.6 1122.73   118.7 1123.02
     122 1122.63   125.3  1121.5   135.4 1116.35     152 1105.05   170.6  1095.1
   178.7 1092.64  190.17 1090.83   198.7 1089.75  217.28 1090.83   252.1 1089.81
     289 1089.88   305.7 1091.57   308.9 1092.38   315.5  1096.6   318.9 1098.18
   325.6 1099.26   328.9 1100.78   338.1 1107.03   352.3 1114.62   428.2 1143.85
#Mann= 5 ,-1,0
       0      .1       0      50     .06       0  190.17    .045       0
  217.28     .06       0     260      .1       0
Bank Sta=190.17,217.28
XS Rating Curve= 0 ,0
Exp/Cntr(USF)=0,0
Exp/Cntr=0.3,0.1

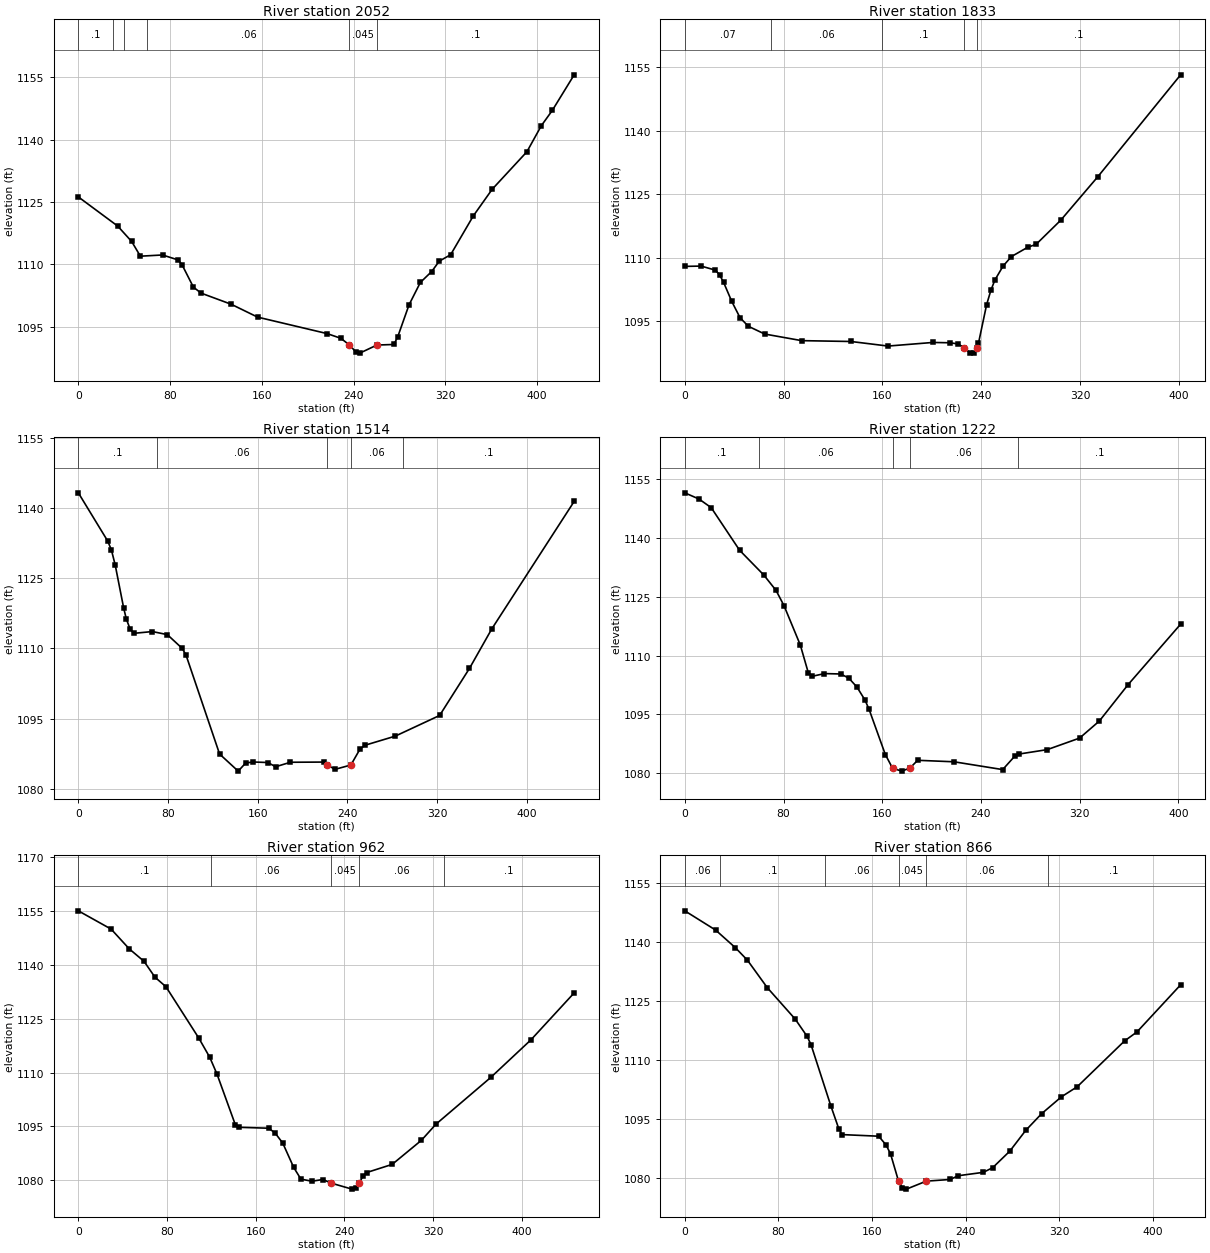
Type RM Length L Ch R = 1 ,2052    ,219.4,219.6,218.6
XS GIS Cut Line= 2
1672162.34845503494256.186984276 1671732.3705472 494211.47728583
#Sta/Elev= 30
       0 1126.22    34.3 1119.22    46.5 1115.51    54.1 1111.98    73.4 1112.27
    87.1 1111.07    90.4 1109.93   100.3 1104.56   106.9 1103.12   133.3 1100.43
   156.3 1097.34   216.8 1093.39   228.9 1092.25  236.411090.634   242.1 1088.94
   245.4 1088.69   260.3 1090.63   275.1 1090.77   278.4 1092.55   288.3 1100.27
   298.2 1105.67   308.1  1108.3   314.7 1110.79   324.6 1112.33   344.4 1121.67
   360.9 1128.08   391.1 1137.07   403.7 1143.34   413.2 1146.98   432.3 1155.55
#Mann= 6 ,-1,0
       0      .1       0      30     .06       0      40      .1       0
      60     .06       0  236.41    .045       0   260.3      .1       0
Bank Sta=236.41,260.3
XS Rating Curve= 0 ,0
Exp/Cntr(USF)=0,0
Exp/Cntr=0.3,0.1

Type RM Length L Ch R = 1 ,1833    ,314.3,318.2,315.9
XS GIS Cut Line= 2
1672149.34042052494052.868070046 1671753.6302071493985.994419504
#Sta/Elev= 30
       0 1107.91    13.2 1107.98    24.7 1107.03    28.1 1105.94    31.4 1104.14
      38 1099.63    44.7 1095.79    51.4 1093.76    64.7 1091.92    94.6 1090.36
   134.5 1090.16   164.5 1089.08   200.7 1089.93   214.4 1089.86     221  1089.6
  226.24 1088.66     231 1087.41   234.4  1087.5  236.111088.659   237.7 1089.76
   244.3 1098.89   247.7 1102.23     251 1104.71   257.6 1107.98   264.3 1110.22
   277.6 1112.44   284.3 1113.11   304.2  1118.8   334.2 1129.07   401.3 1153.18
#Mann= 5 ,-1,0
       0     .07       0      70     .06       0     160      .1       0
  226.24    .045       0  236.11      .1       0
Bank Sta=226.24,236.11
XS Rating Curve= 0 ,0
Exp/Cntr(USF)=0,0
Exp/Cntr=0.3,0.1

Type RM Length L Ch R = 1 ,1514    ,287.6,292.6,287.3
XS GIS Cut Line= 2
1672209.85450079493771.1137603911671773.62707467493698.141461616
#Sta/Elev= 30
       0 1143.32    26.2    1133    29.5 1131.09    32.9 1127.86    40.4 1118.71
    42.8 1116.31    46.2 1114.16    49.5 1113.24    66.1 1113.62    79.4 1112.96
    92.7 1110.01    96.1 1108.56     126  1087.4   142.6 1083.74   149.3 1085.48
   155.9  1085.7   169.2 1085.58   175.9 1084.67   189.2 1085.64   219.1 1085.68
  221.88 1085.05   229.1 1084.13  243.12 1085.05   251.3 1088.47   255.7 1089.28
   282.7 1091.23   322.3 1095.66   348.9 1105.73   368.8 1114.18   442.3 1141.48
#Mann= 5 ,-1,0
       0      .1       0      70     .06       0  221.88    .045       0
  243.12     .06       0     290      .1       0
Bank Sta=221.88,243.12
XS Rating Curve= 0 ,0
Exp/Cntr(USF)=0,0
Exp/Cntr=0.3,0.1

Type RM Length L Ch R = 1 ,1222    ,248.2,260,248.8
XS GIS Cut Line= 2
1672254.60638125493517.6325896541671852.83037476493516.890560508
#Sta/Elev= 30
       0 1151.52    11.5 1149.94    21.4 1147.74    44.4 1136.88      64 1130.57
    73.9 1126.66    80.4 1122.75    93.6 1112.72   100.1 1105.62   103.4 1104.75
   113.2 1105.43   126.4 1105.33   132.9 1104.27   139.5    1102     146 1098.69
   149.3 1096.34   162.5 1084.79  168.361081.311   175.7 1080.56  182.38 1081.32
   188.7 1083.32   218.2 1082.94   257.6 1080.95   267.4 1084.38   270.7 1084.91
   293.7 1086.04   319.9 1088.98   335.9 1093.32   359.3 1102.64   401.8 1118.03
#Mann= 5 ,-1,0
       0      .1       0      60     .06       0  168.36    .045       0
  182.38     .06       0     270      .1       0
Bank Sta=168.36,182.38
XS Rating Curve= 0 ,0
Exp/Cntr(USF)=0,0
Exp/Cntr=0.3,0.1

Type RM Length L Ch R = 1 ,962     ,91.8,96,87.4
XS GIS Cut Line= 2
1672285.66645133493282.9887973371671840.02561034 493319.28798224
#Sta/Elev= 30
       0 1155.05    29.6 1149.95      46 1144.43    59.2    1141    69.1 1136.57
      79 1133.91   108.6 1119.62   118.5 1114.26     125 1109.61   141.5 1095.53
   144.8 1094.76   171.8  1094.5   177.7 1093.06   184.3 1090.38   194.2 1083.59
   200.7 1080.33   210.6 1079.74   220.5 1080.22  228.24 1079.19   246.8 1077.54
   250.1 1077.74   253.4 1079.19   256.7 1081.26     260 1082.16     283 1084.43
   309.4 1091.15   322.5 1095.63   371.9 1108.65   408.1 1119.11   447.1 1132.19
#Mann= 5 ,-1,0
       0      .1       0     120     .06       0  228.24    .045       0
   253.4     .06       0     330      .1       0
Bank Sta=228.24,253.4
XS Rating Curve= 0 ,0
Exp/Cntr(USF)=0,0
Exp/Cntr=0.3,0.1

Type RM Length L Ch R = 1 ,866     ,134.2,139,140.1
XS GIS Cut Line= 2
1672255.39897649493171.881671272 1671846.1483904493280.870804429
#Sta/Elev= 30
       0 1147.82    26.4 1142.92    43.3 1138.43    53.5 1135.29    70.5  1128.3
    94.3 1120.34   104.4 1115.99   107.8 1113.86   124.8 1098.27   131.6 1092.45
   134.3 1091.03   165.6 1090.62   171.9  1088.4   175.7 1086.16  182.56 1079.22
   185.9 1077.48   189.3 1077.19   206.3 1079.22   226.7 1079.64   233.5 1080.59
     255 1081.45     263 1082.64   277.6 1086.83   291.2  1092.1   304.8 1096.34
   321.7 1100.62   335.2 1103.18   375.6  1114.8   386.2 1117.08   423.5 1129.04
#Mann= 6 ,-1,0
       0     .06       0      30      .1       0     120     .06       0
  182.56    .045       0   206.3     .06       0     310      .1       0
Bank Sta=182.56,206.3
XS Rating Curve= 0 ,0
Exp/Cntr(USF)=0,0
Exp/Cntr=0.3,0.1

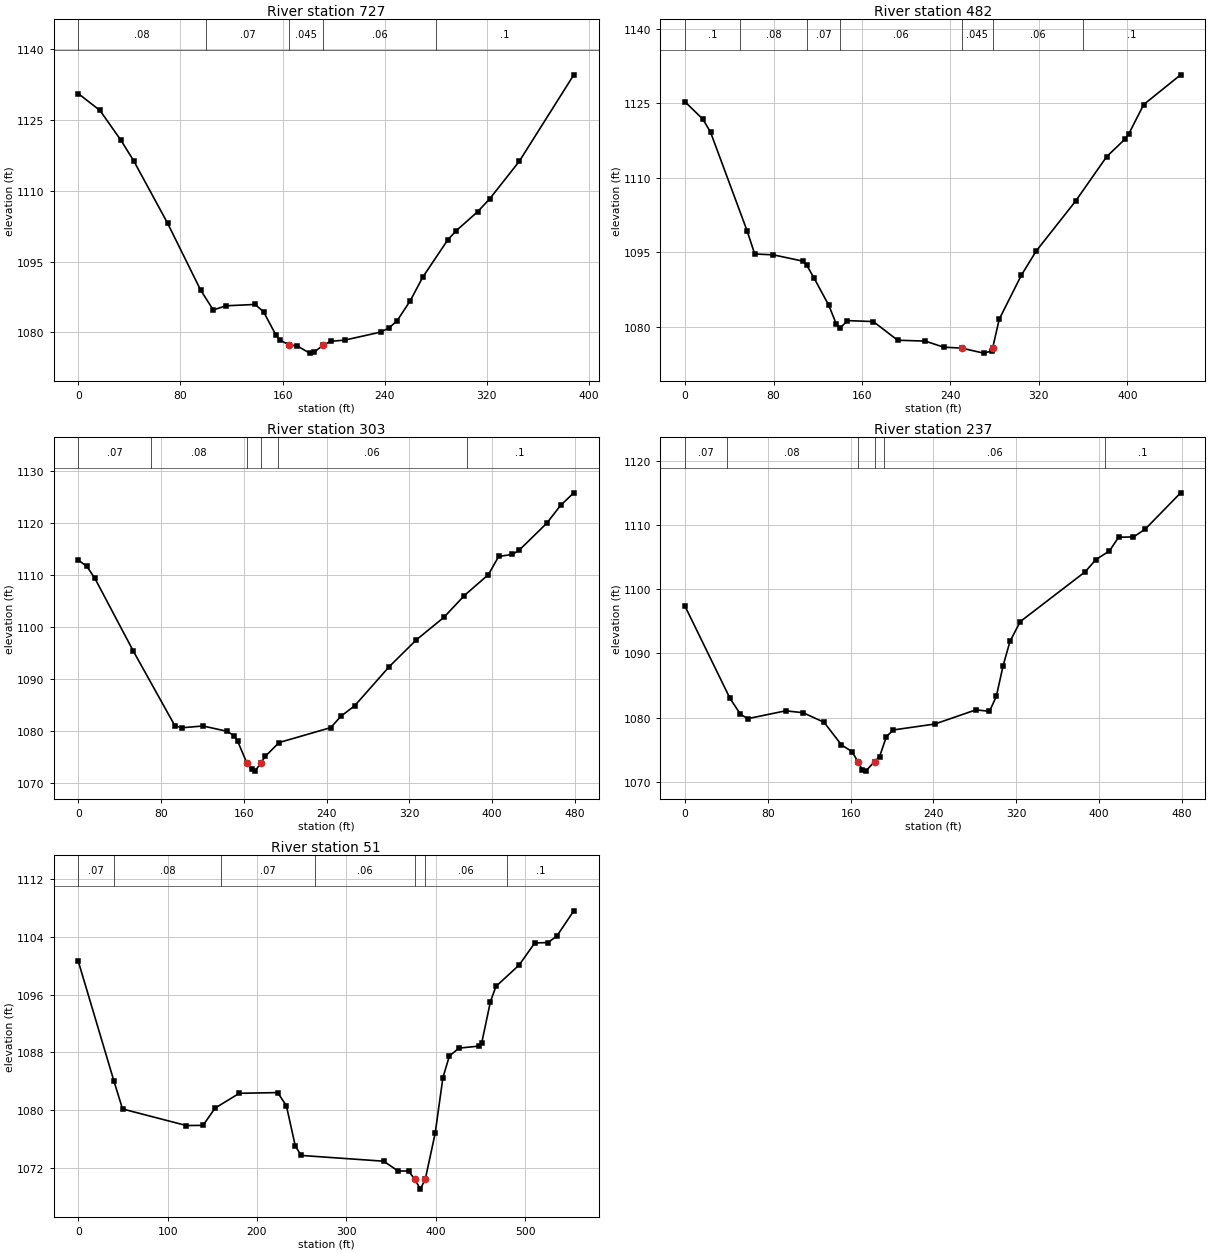
Type RM Length L Ch R = 1 ,727     ,221.4,245.2,239.8
XS GIS Cut Line= 2
1672204.27399557493087.5833774991671816.50957732493103.791668601
#Sta/Elev= 30
       0 1130.63      17 1127.05    33.4 1120.73    43.3 1116.42      70 1103.12
    95.8 1088.98   105.7 1084.77   115.5 1085.65   138.5 1085.94   145.1 1084.38
   154.9 1079.39   158.2 1078.34  165.271077.337   171.3 1077.17   181.2 1075.62
   184.5 1075.79     1921077.338   197.6 1078.12   208.7 1078.38     237 1080.09
   243.6 1081.01   249.7 1082.49     260 1086.72   269.8 1091.73   289.5 1099.67
   296.1 1101.59   312.7 1105.57   322.4 1108.38   345.4 1116.28   388.1 1134.61
#Mann= 5 ,-1,0
       0     .08       0     100     .07       0  165.27    .045       0
     192     .06       0     280      .1       0
Bank Sta=165.27,192
XS Rating Curve= 0 ,0
Exp/Cntr(USF)=0,0
Exp/Cntr=0.3,0.1

Type RM Length L Ch R = 1 ,482     ,171.7,179,177.5
XS GIS Cut Line= 2
1672245.61665314 492968.006394211671806.78875344492876.586672395
#Sta/Elev= 30
       0 1125.24      16 1121.77      23 1119.12    56.2 1099.17    62.9 1094.61
    79.7 1094.44   106.5 1093.17   109.9 1092.37   116.6 1089.77     130 1084.24
   136.7 1080.51     140 1079.62   146.7 1081.19   170.2    1081   192.2 1077.24
   217.2 1077.06   233.8 1075.84  250.351075.643   269.9 1074.64   277.4 1075.07
  278.121075.646   284.1 1081.47   304.2 1090.37   317.6 1095.22   353.1 1105.24
   381.3 1114.22   398.1  1117.8   401.4 1118.85   414.8 1124.72   448.2  1130.7
#Mann= 7 ,-1,0
       0      .1       0      50     .08       0     110     .07       0
     140     .06       0  250.35    .045       0  278.12     .06       0
     360      .1       0
Bank Sta=250.35,278.12
XS Rating Curve= 0 ,0
Exp/Cntr(USF)=0,0
Exp/Cntr=0.3,0.1

Type RM Length L Ch R = 1 ,303     ,65.3,65.5,66.1
XS GIS Cut Line= 6
1672238.95249454492812.9102945431672153.49826912492793.631789799
1672080.46396638492776.098688375 1671981.3375242492759.251281123
1671880.00603395492772.1357697951671767.82351554492790.181009288
#Sta/Elev= 30
       0  1112.8     8.2 1111.63      16 1109.31      53 1095.37    93.3 1080.96
   100.1 1080.55   120.5  1080.9     144 1079.86   150.7 1078.99   154.1 1077.95
  162.861073.801   167.5 1072.54   170.8 1072.21   176.61073.801   180.8 1075.07
   194.1 1077.71     244 1080.58     254 1082.79   267.2 1084.79   300.4 1092.28
   326.8 1097.47   353.3 1101.78   373.2    1106   396.4 1110.02   406.4 1113.52
   419.7 1113.91   426.3 1114.74   452.8  1119.9   466.2 1123.34     479 1125.76
#Mann= 6 ,-1,0
       0     .07       0      70     .08       0  162.86    .045       0
   176.6     .08       0  192.71     .06       0  375.41      .1       0
Bank Sta=162.86,176.6
XS Rating Curve= 0 ,0
Exp/Cntr(USF)=0,0
Exp/Cntr=0.3,0.1

Type RM Length L Ch R = 1 ,237     ,186.5,186.4,176.5
XS GIS Cut Line= 6
1672232.80384666492750.3668430861672147.34962124492731.088338342
 1672074.3153185492713.5552369171671975.18887632492696.707829665
1671873.85738607492709.5923183371671761.67486766492727.637557831
#Sta/Elev= 30
       0 1097.31    43.3    1083    53.4 1080.52    60.5 1079.82    97.1 1081.04
     114 1080.75   134.3 1079.25   151.1 1075.73   161.2 1074.69  167.021073.128
   171.3 1071.84   174.6 1071.64  183.091073.129   187.9 1073.87   194.5    1077
   201.2 1078.06   241.3 1078.98     281 1081.19   294.2 1080.97   300.8 1083.28
   307.4 1088.09     314 1091.86     324 1094.96   386.9 1102.74   396.9  1104.6
   410.2 1105.97     419 1108.11   433.4 1108.15   444.7 1109.36     479 1115.03
#Mann= 6 ,-1,0
       0     .07       0      40     .08       0  167.02    .045       0
  183.09     .08       0  192.71     .06       0  405.41      .1       0
Bank Sta=167.02,183.09
XS Rating Curve= 0 ,0
Exp/Cntr(USF)=0,0
Exp/Cntr=0.3,0.1

Type RM Length L Ch R = 1 ,51      ,,,
XS GIS Cut Line= 4
1672252.46493649492744.4394312351672103.95005197492603.625318501
1671948.83450591492613.5263108021671771.71675474492693.834359471
#Sta/Elev= 30
       0  1100.6      40 1083.96    49.5 1080.15     121 1077.85   139.6 1077.88
   153.1 1080.27   180.2 1082.32   223.1 1082.42   232.9 1080.59   242.8 1075.05
   249.4 1073.71   341.8 1072.91   357.9 1071.55   369.6 1071.55  376.311070.465
   382.9 1069.04  388.441070.466   399.4 1076.76   408.1 1084.49   415.3 1087.49
   426.1 1088.58   448.9 1088.87   451.6 1089.34   461.3 1095.04   467.5 1097.14
   493.5 1100.11   510.9 1103.16   525.8 1103.21   535.7 1104.13   554.6 1107.61
#Mann= 7 ,-1,0
       0     .07       0      40     .08       0     160     .07       0
  264.66     .06       0  376.31    .045       0  388.44     .06       0
  480.09      .1       0
Bank Sta=376.31,388.44
XS Rating Curve= 0 ,0
Exp/Cntr(USF)=0,0
Exp/Cntr=0.3,0.1
LCMann Table=0

Chan Stop Cuts=-1
Use User Specified Reach Order=0
Composite Channel Slope=5